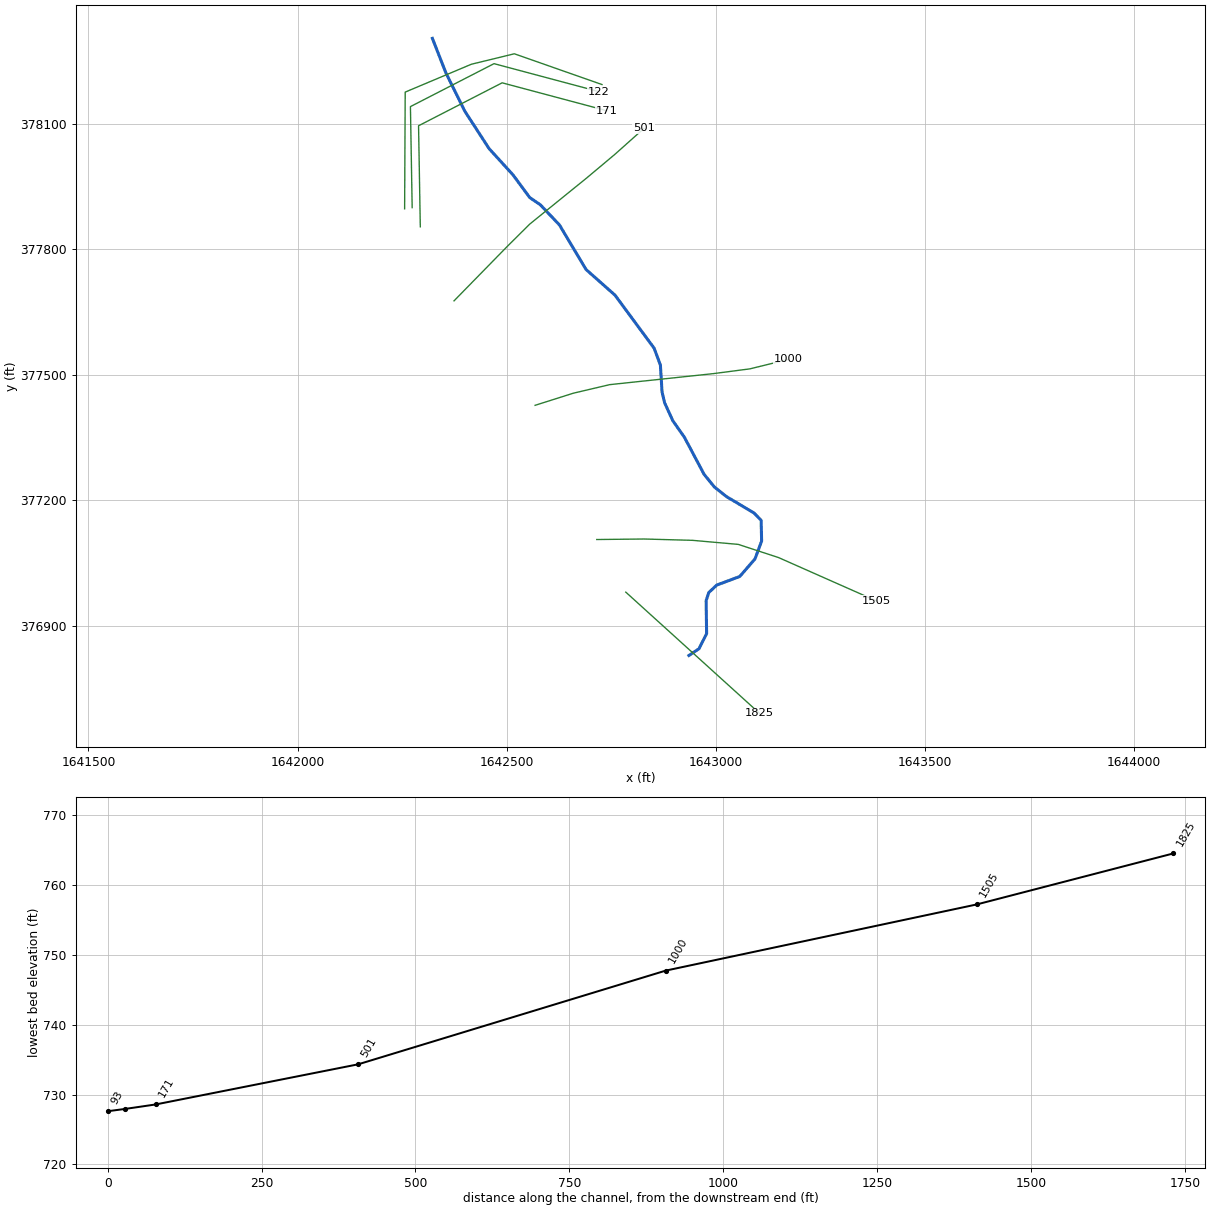
--- WYATTRN.prj (project) ---

Proj Title=WYATTRN
Current Plan=p01
Default Exp/Contr=0.3,0.1
English Units
Geom File=g01
Flow File=f01
Plan File=p01
Y Axis Title=Elevation
X Axis Title(PF)=Main Channel Distance
X Axis Title(XS)=Station
BEGIN DESCRIPTION:
---------- MODELED AS PART OF WVEMD CTP PROGRAM, 2023----------
Stream Name: Wyatt Run
Flood Zone:  AFH
Wetzel County, WV
HEC-RAS Version: RAS 6.3
Vertical Datum: NAVD88
Projection: NAD 1983 StatePlane West Virginia S FIPS 4702 (US Feet)
Terrain: 1-meter West Virginia FEMA R3 South Central (collected 2018-2020)
Land Use: 2019 NLCD
Hydrologic Method:
WV 2010 Regional Regression Equations
Additional Model Notes:
None
END DESCRIPTION:
DSS Export Rating Curves= 0
DSS Export Rating Curve Sorted= 0
DSS Export Volume Flow Curves= 0
DXF OffsetX= 0
DXF OffsetY= 0
DXF ScaleX= 1
DXF ScaleY= 10

--- WYATTRN.p01 (plan) ---

Plan Title=Floodplain
Program Version=6.31
Short Identifier=Floodplain
Geom File=g01
Flow File=f01
Subcritical Flow
K Sum by GR= 0
Std Step Tol= 0.01
Critical Tol= 0.01
Num of Std Step Trials= 20
Max Error Tol= 0.3
Flow Tol Ratio= 0.001
Split Flow NTrial= 30
Split Flow Tol= 0.02
Split Flow Ratio= 0.02
Log Output Level= 0
Friction Slope Method= 1
Unsteady Friction Slope Method= 2
Unsteady Bridges Friction Slope Method= 1
Parabolic Critical Depth
Global Vel Dist= 0 , 0 , 0
Global Log Level= 0
CheckData=True
Encroach Param=-1 ,0,0, 0
Computation Interval=1MIN
Output Interval=1HOUR
Instantaneous Interval=1HOUR
Mapping Interval=1HOUR
Computation Time Step Use Courant=        0
Computation Time Step Use Time Series=    0
Computation Time Step Count To Double=0
Computation Time Step Max Doubling=0
Computation Time Step Max Halving=0
Computation Time Step Residence Courant=0
Run HTab= 0
Run UNet= 0
Run Sediment= 0
Run PostProcess= 0
Run WQNet= 0
Run RASMapper= 0
UNET Theta= 1
UNET Theta Warmup= 1
UNET ZTol= 0.02
UNET ZSATol= 0.02
UNET MxIter= 20
UNET Max Iter WO Improvement= 0
UNET MaxInSteps= 0
UNET DtIC= 0
UNET DtMin= 0
UNET MaxCRTS= 20
UNET WFStab= 2
UNET SFStab= 1
UNET WFX= 1
UNET SFX= 1
UNET Gravity=32.17405
UNET 1D Methodology=Finite Difference
UNET DSS MLevel= 4
UNET Pardiso=0
UNET DZMax Abort= 100
UNET Use Existing IB Tables=-1
UNET Froude Reduction=False
UNET Froude Limit= 0.8
UNET Froude Power= 4
UNET D1 Cores= 0
UNET WindReference=Eulerian
UNET WindDragFormulation=Hsu (1988)
UNET D2 Coriolis=0
UNET D2 Cores= 0
UNET D2 Theta= 1
UNET D2 Theta Warmup= 1
UNET D2 Z Tol= 0.01
UNET D2 Volume Tol= 0.01
UNET D2 Max Iterations= 20
UNET D2 Equation= 0
UNET D2 RampUpFraction=0.1
UNET D2 TimeSlices= 1
UNET D2 Turbulence Formulation=None
UNET D2 Eddy Viscosity=0.3
UNET D2 Transverse Eddy Viscosity=0.1
UNET D2 Smagorinsky Mixing=0.05
UNET D2 BCVolumeCheck=0
UNET D2 Cores=0
UNET D2 SolverType=PARDISO (Direct)
UNET D2 Minimum Iterations= 3
UNET D2 Maximum Iterations= 30
UNET D2 Restart Number= 10
UNET D2 Relaxation Coeff=1.3
UNET D2 SOR Precondition Iterations= 10
UNET D2 ILUT Maximum Fill= 8
UNET D2 ILUT Tolerance=1E-08
UNET D2 Convergence Tolerance=0.00001
UNET D1D2 MaxIter= 0
UNET D1D2 ZTol=0.01
UNET D1D2 QTol=0.1
UNET D1D2 MinQTol=1
Write IC File= 0
Write IC File at Fixed DateTime=0
Write IC File at Sim End=0
Echo Input=False
Echo Parameters=False
Echo Output=False
Write Detailed= 0
HDF Write Warmup=0
HDF Write Time Slices=0
HDF Flush=0
HDF Compression= 1
HDF Chunk Size= 1
HDF Spatial Parts= 1
HDF Use Max Rows=0
HDF Fixed Rows= 1
Calibration Method= 0
Calibration Iterations= 20
Calibration Max Change=0.05
Calibration Tolerance=0.2
Calibration Maximum=1.5
Calibration Minimum=0.5
Calibration Optimization Method= 1
WQ AD Non Conservative
WQ ULTIMATE=-1
WQ Max Comp Step=1HOUR
WQ Output Interval=15MIN
WQ Output Selected Increments= 0
WQ Create Restart=0
WQ Fixed Restart=0
WQ System Summary=0
WQ Write To DSS=0
Sorting and Armoring Iterations= 10
XS Update Threshold= 0.02
Bed Roughness Predictor= 0
Hydraulics Update Threshold= 0.02
Energy Slope Method= 1
Volume Change Method= 1
Sediment Retention Method= 0
Sediment TS Multiplier= 1
Warm Up Method= 0
XS Weighting Method= 0
Number of US Weighted Cross Sections= 1
Number of DS Weighted Cross Sections= 1
Upstream XS Weight=0
Main XS Weight=1
Downstream XS Weight=0
Number of DS XS's Weighted with US Boundary= 1
Upstream Boundary Weight= 1
Weight of XSs Associated with US Boundary= 0
Number of US XS's Weighted with DS Boundary= 1
Downstream Boundary Weight= 0.5
Weight of XSs Associated with DS Boundary= 0.5
Percentile Method= 0
Sediment Output Level= 3
Mass or Volume Output= 0
Output Increment Type= 1
Profile and TS Output Increment= 1
Transport Output Increment 1
XS Output Flag= 0
XS Output Increment= 10
Read HDF5 Sediment Hotstart= 0
Sediment Hotstart Type= 0
Write Gradation File= 0
Read Gradation Hotstart= 0
Write HDF5 File= 1
Write Binary Output= 1
Write DSS Sediment File= 0
DSS Sediment Output Type= 1
SV Curve= 0
Specific Gage Flag= 0
Subcell Erosion Methods= 0
Subcell Deposition Methods= 0
Advection Scheme= 1
Matrix Solver= 0
Implicit Weighting Factor= 1
Maximum Outer Loop Convergence Iterations= 5
Convergence Maximum Absolute= 0.001
Convergence RMSE= 0.0001
Grain Fractions Max Abs Error= 0.001
Max Subgrid Regions= 1
Max Subgrid Length Scale= 3.402823E+38
Initial Layer Thickness= 3.402823E+38
Min Layer Thickness= 3.402823E+38
Max Layer Thickness= 3.402823E+38
Number of Layers= 5

--- WYATTRN.f01 (steady flow) ---

Flow Title=Flow
Program Version=6.31
Number of Profiles= 1
Profile Names=F01pct
River Rch & RM=WYATTRN,Main            ,1825
     576
Boundary for River Rch & Prof#=WYATTRN,Main            , 1
Up Type= 0
Dn Type= 3
Dn Slope=0.01163
DSS Import GetInterval= 0
DSS Import GetPeak= 0
DSS Import FillOption= 0

--- WYATTRN.g01 (geometry) ---

Geom Title=Geometry
Program Version=6.31

River Reach=WYATTRN         ,Main
Reach XY= 30
1642935.89181764376828.5402762291642960.06007639376844.784666315
1642978.28510556376880.8390561491642977.09678772 376959.68305856
1642983.43601389376979.0970617231643002.45369239376996.926094309
1643057.52543263377017.5284153071643093.97614713377059.525706649
1643109.82421255377102.3156473041643108.63556664377151.840810731
 1643091.5988553377169.273846731 1643025.8293018377208.497521564
1642996.90678747377231.4774624711642972.34220405377261.588622734
1642925.19433247377350.3377890591642897.46013597377389.958116651
 1642878.0461328377432.3514045631642871.70690663377458.500958562
 1642867.7449723377523.0818661451642852.68922813377563.494186893
1642759.18580621377690.2787102311642689.85064305377751.690004721
1642626.43344705 377858.094975651642580.62284313377906.381952554
1642555.24100414377923.7159073951642515.00191139377978.193488732
1642458.04795705 378040.718954221642399.85581622378130.483538479
1642354.66397747378222.1050743911642322.44914688378304.421838894

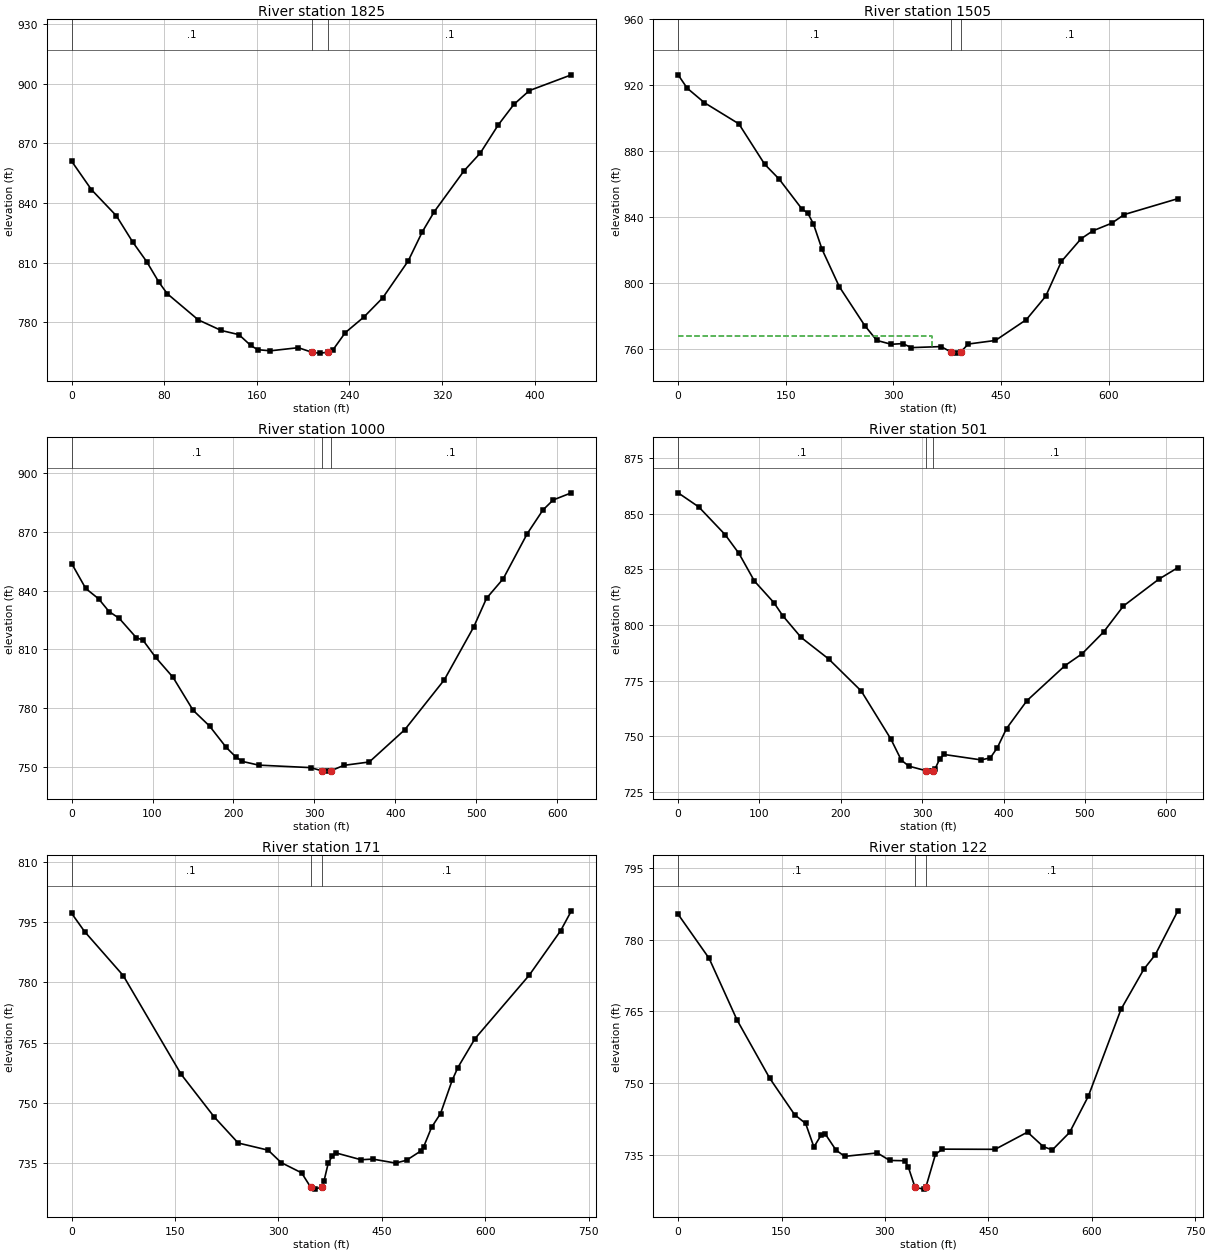
Type RM Length L Ch R = 1 ,1825    ,314.5,319.8,320.9
XS GIS Cut Line= 2
1642785.04407599376980.0322114841643104.90398396376690.159169887
#Sta/Elev= 30
       0  861.07    17.1  846.76    38.6  833.64    52.8  820.38    64.8  810.57
    75.4  800.18    82.6  794.41   109.4  781.25   129.2  775.92   144.5  773.82
   154.7  768.37   160.7  766.25   171.7  765.69   195.8  767.26   207.7  764.93
   214.2  764.52  221.29  764.93   225.5  765.98   236.3  774.78   252.5  782.72
   268.7  792.33   290.7  810.89     303  825.66   313.3  835.75   338.8  856.14
     353  865.19   368.6  879.42     382  889.67   395.4  896.62431.6674  904.55
#Mann= 3 ,-1,0
       0      .1       0   207.7    .045       0  221.29      .1       0
Bank Sta=207.7,221.29
XS Rating Curve= 0 ,0
Exp/Cntr(USF)=0,0
Exp/Cntr=0.3,0.1

Type RM Length L Ch R = 1 ,1505    ,495.9,505.1,502.9
XS GIS Cut Line= 6
1642715.55301951377105.899629667  1642828.853974377107.138800427
1642944.43051451377103.9672188461643053.94735584377094.277277589
1643150.11645484377062.8153982611643384.41913584376959.054122835
#Sta/Elev= 30
       0  926.37    12.6  918.27    36.6  909.44    84.6  896.59   120.6  872.02
   140.6  863.08   172.6  844.79   180.6  842.36   188.6   835.7   200.6  820.26
   224.6  797.59     260  773.99   276.8  764.94   296.9  762.59     313     763
     325  760.56   366.4  761.19     380  757.95   387.4  757.21  393.83  757.95
   404.3  762.74   442.2  764.92   485.2  777.56   512.2  791.79   534.1  812.95
   561.5  826.75   577.9  831.54   604.1  836.17   621.6  841.44696.3073   851.1
#Mann= 3 ,-1,0
       0      .1       0     380    .045       0  393.83      .1       0
#XS Ineff= 2 , 0
          354.28  767.81
Permanent Ineff=
       F       F
Bank Sta=380,393.83
XS Rating Curve= 0 ,0
Exp/Cntr(USF)=0,0
Exp/Cntr=0.3,0.1

Type RM Length L Ch R = 1 ,1000    ,498.6,499.5,504.6
XS GIS Cut Line= 6
1642568.03789459377426.8209038381642659.54886642377455.817565009
1642746.40466385377476.2420648341642995.03211933377502.683284923
 1643081.8360796377514.0290627631643173.94547543377536.646143511
#Sta/Elev= 30
       0  853.88    17.4  841.12    33.3  835.85    46.2  829.34    58.8  825.85
    79.8  816.01    88.2  814.67   103.7  805.95   125.3   795.7     150   778.9
   170.5  770.76     191   759.9     203  754.95     211  752.71   231.1  750.81
   295.5  749.53  309.14  747.92   315.6  747.74  320.31  747.92   336.5  750.69
   367.9  752.42   411.7   768.9   460.6  794.42   496.9  821.41   512.8  836.12
   533.4  846.09   563.1  869.14   582.5  881.24   595.2  886.38617.6438  890.02
#Mann= 3 ,-1,0
       0      .1       0  309.14    .045       0  320.31      .1       0
Bank Sta=309.14,320.31
XS Rating Curve= 0 ,0
Exp/Cntr(USF)=0,0
Exp/Cntr=0.3,0.1

Type RM Length L Ch R = 1 ,501     ,330.8,329.1,327.6
XS GIS Cut Line= 6
1642374.27023751377676.6688293371642501.84478551377807.078345418
1642555.36633201377860.2353913341642691.34768733 377970.39527601
1642758.42235634378026.5877489151642828.42615335378088.994448259
#Sta/Elev= 30
       0   859.3    25.4  852.96    57.8  840.51    74.8  832.06    93.8  819.66
   117.6  810.03   128.7  804.07   151.2  794.35   185.1  784.67   225.1  770.29
   261.5  748.72   274.3  739.26   283.6  736.57   304.1  734.57   308.9  734.33
  312.78  734.57   315.5  735.13   321.5  739.79   326.8  741.81   372.4  739.37
   383.7  740.29   392.3  744.84   403.6  753.44   428.7  765.97   475.6  781.74
   496.5  787.03     523  796.84   547.3  808.49   590.9  820.55614.1581  825.69
#Mann= 3 ,-1,0
       0      .1       0   304.1    .045       0  312.78      .1       0
Bank Sta=304.1,312.78
XS Rating Curve= 0 ,0
Exp/Cntr(USF)=0,0
Exp/Cntr=0.3,0.1

Type RM Length L Ch R = 1 ,171     ,49.6,49.6,49.6
XS GIS Cut Line= 4
1642293.58209704377853.7644966521642289.41725449378095.325364649
1642489.32969697378198.0581475911642739.22025007378131.420666764
#Sta/Elev= 30
       0  797.16    18.8  792.64    74.8   781.7   158.8  757.15   206.8  746.54
   241.6  740.05   285.1  738.27   303.9  735.19   333.6  732.63   346.8  729.05
   352.6  728.58  362.54  729.05   366.1   730.6   372.2  735.01   378.2  736.83
     384  737.56   419.8  735.89   436.8  736.05   469.9  735.06   485.8  735.76
   506.5  738.06   510.6  739.07   522.2  743.96   535.2  747.39     552  755.62
   560.3  758.82   585.2  766.02   663.8  781.78   709.4  792.85724.9841   797.8
#Mann= 3 ,-1,0
       0      .1       0   346.8    .045       0  362.54      .1       0
Bank Sta=346.8,362.54
XS Rating Curve= 0 ,0
Exp/Cntr(USF)=0,0
Exp/Cntr=0.3,0.1

Type RM Length L Ch R = 1 ,122     ,29.2,28.4,27.9
XS GIS Cut Line= 4
1642274.14616513377899.5777647211642269.98132258378141.138632718
1642469.89376506378243.8714156591642719.78431816378177.233934832
#Sta/Elev= 30
       0  785.26      45  776.06    85.5  763.21     133  751.04     169  743.47
     185  741.63     197  736.73   207.4  739.18     213  739.54     229  736.09
   241.6  734.77     289  735.49     307  733.92   328.9  733.86   333.9  732.57
   343.7  728.32   356.4  727.94  359.39  728.33   373.4  735.21   383.4  736.28
   459.9  736.24   506.9  739.83   529.7  736.82   542.8   736.1     568  739.77
   595.1  747.31   642.5  765.43   675.6  773.79   692.2  776.81724.9841  785.98
#Mann= 3 ,-1,0
       0      .1       0   343.7    .045       0  359.39      .1       0
Bank Sta=343.7,359.39
XS Rating Curve= 0 ,0
Exp/Cntr(USF)=0,0
Exp/Cntr=0.3,0.1

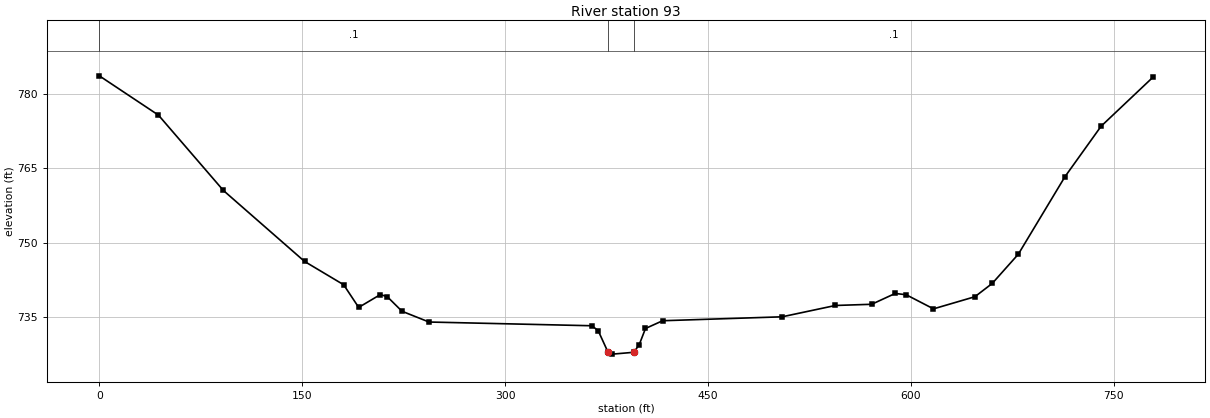
Type RM Length L Ch R = 1 ,93      ,,,
XS GIS Cut Line= 5
1642256.09851407 377896.801203021642257.48679492378175.845653982
1642415.75081189378242.4831348091642518.48359483378267.472190119
1642728.11400326378193.893305039
#Sta/Elev= 30
       0  783.61    43.7   775.7    91.7  760.54   151.7  746.26   180.6  741.57
   191.7  737.01   207.7  739.59   212.8  739.18   223.7  736.24   243.7  734.07
     364  733.32   368.7  732.35  376.05  727.98   379.3  727.61   395.1  727.98
   399.1  729.53   403.7  732.77   416.4  734.33   504.7  735.12   544.1   737.4
   570.9  737.64   588.3  739.82   596.4  739.56   616.6  736.72   647.2  739.16
     660  741.83   679.3  747.72   713.8  763.32   740.5  773.47778.6654  783.29
#Mann= 3 ,-1,0
       0      .1       0  376.05    .045       0   395.1      .1       0
Bank Sta=376.05,395.1
XS Rating Curve= 0 ,0
Exp/Cntr(USF)=0,0
Exp/Cntr=0.3,0.1
LCMann Table=0

Chan Stop Cuts=-1
Use User Specified Reach Order=0
Composite Channel Slope=5